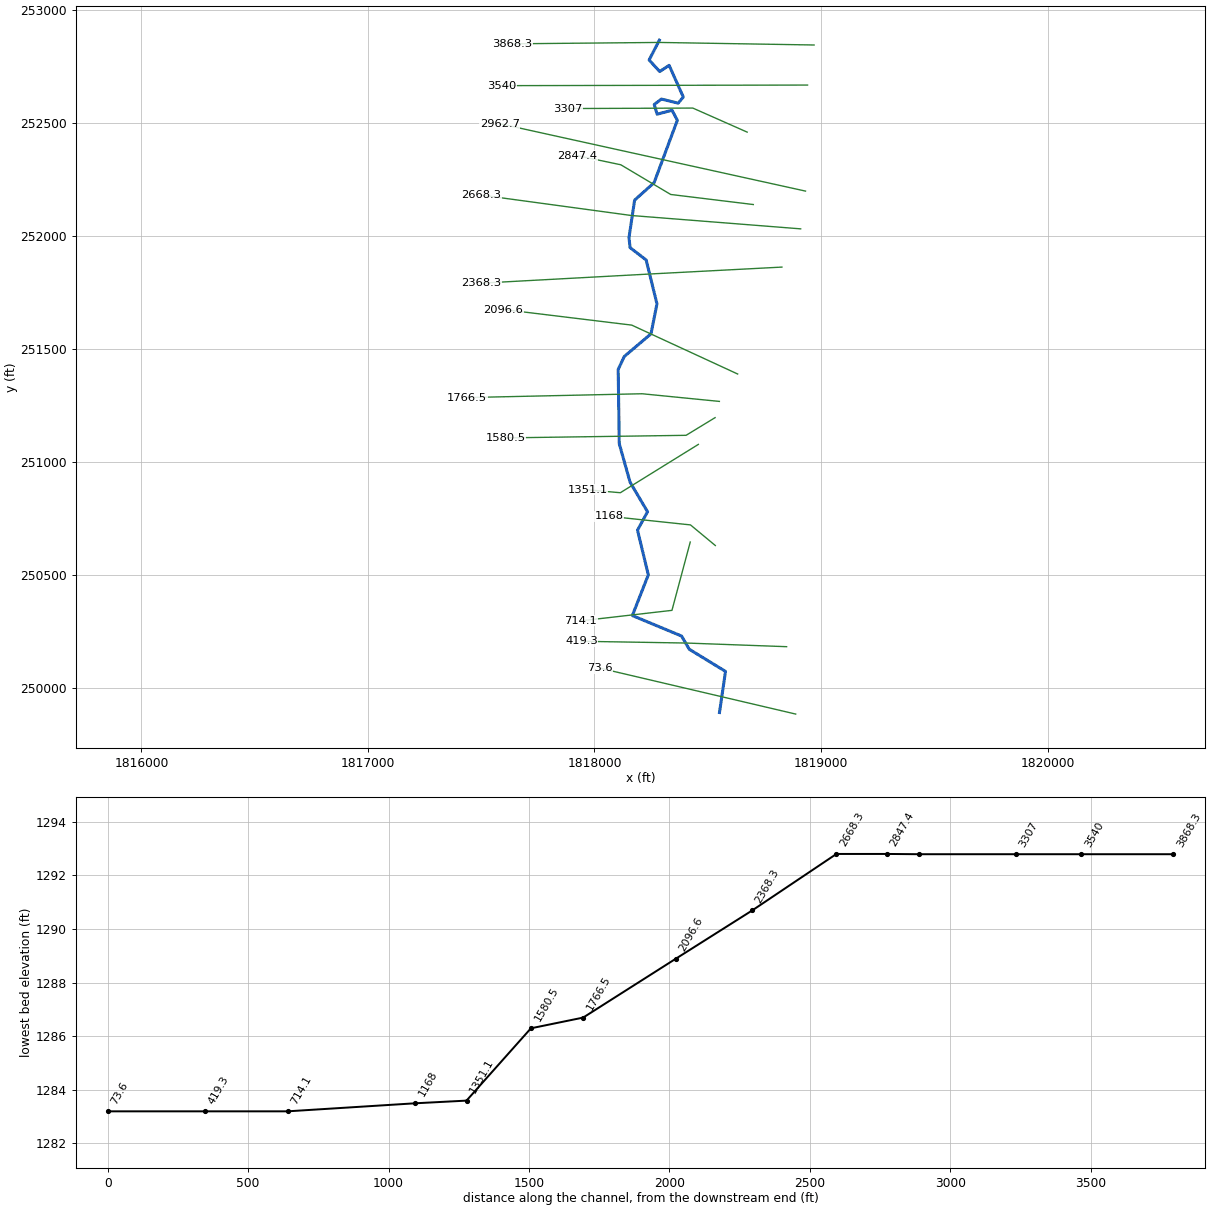
--- TAYLORDR.prj (project) ---

Proj Title=TAYLORDR
Current Plan=p01
Default Exp/Contr=0,0
English Units
Geom File=g01
Flow File=f01
Plan File=p01
BEGIN DESCRIPTION:
END DESCRIPTION:
DSS Export Rating Curves= 0
DSS Export Rating Curve Sorted= 0
DSS Export Volume Flow Curves= 0
DXF OffsetX= 0
DXF OffsetY= 0
DXF ScaleX= 0
DXF ScaleY= 0

--- TAYLORDR.p01 (plan) ---

Plan Title=Floodplain
Program Version=4.00
Geom File=g01
Flow File=f01
K Sum by GR=0
Std Step Tol=0.01
Critical Tol=0.01
Num of Std Step Trials=20
Max Error Tol=0.3
Flow Tol Ratio=0.001
Split Flow NTrial=30
Split Flow Tol=0.02
Split Flow Ratio=0.02
Log Output Level=0
Friction Slope Method=1
Unsteady Friction Slope Method=2
Unsteady Bridges Friction Slope Method=1
Global Log Level=0
CheckData=False
Run HTab=0
Run UNet=0
Run PostProcess=0
UNET Theta=0
UNET Theta Warmup=0
UNET ZTol=0
UNET ZSATol=0
UNET MxIter=0
UNET MaxInSteps=0
UNET DtIC=0
UNET DtMin=0
UNET MaxCRTS=0
UNET WFStab=0
UNET SFStab=0
UNET WFX=0
UNET SFX=0
UNET DSS MLevel=0
UNET DZMax Abort=0
UNET Convert EG Bridges=0
UNET Use Existing IB Tables=0
UNET Froude Limit=0
UNET Froude Power=0
Write IC File=0
Echo Input=False
Echo Output=False
Write Detailed=0

--- TAYLORDR.f01 (steady flow) ---

Flow Title=NFF Regression Equation
Program Version=4.00
Number of Profiles=1
Profile Names=P100yr
River Rch & RM=TAYLORDR,Main      ,3868.3
507.0506
River Rch & RM=TAYLORDR,Main      ,2962.7
523.5299
River Rch & RM=TAYLORDR,Main      ,419.3
568.6864
River Rch & RM=TAYLORDR,Main      ,73.6
570.3017
Boundary for River Rch & Prof#=TAYLORDR,Main      ,1
Up Type=0
Dn Type=3
Dn Slope=0.000239

--- TAYLORDR.g01 (geometry) ---

Geom Title=USGS 10m DEM
Program Version=4.10

River Reach=TAYLORDR        ,Main
Reach XY= 30
     1818286.324      252864.751     1818241.122      252777.194
      1818287.84      252726.079      1818329.43      252753.582
     1818391.927      252613.515     1818369.321      252586.261
     1818295.441      252604.548     1818263.691      252580.514
     1818276.436      252537.582     1818342.176      252555.023
     1818365.653      252510.751     1818262.968      252234.656
     1818177.088      252157.699     1818152.284      251991.991
     1818157.056      251947.836     1818228.138      251892.939
     1818275.698      251699.145     1818249.388      251566.584
     1818131.383      251466.423     1818104.521      251409.026
      1818109.34      251080.891     1818157.033       250910.88
     1818234.176      250780.073     1818189.807      250698.852
     1818237.526      250501.331     1818167.095      250321.242
     1818384.436      250230.684     1818418.236      250172.421
     1818578.299      250074.386     1818551.676       249892.57

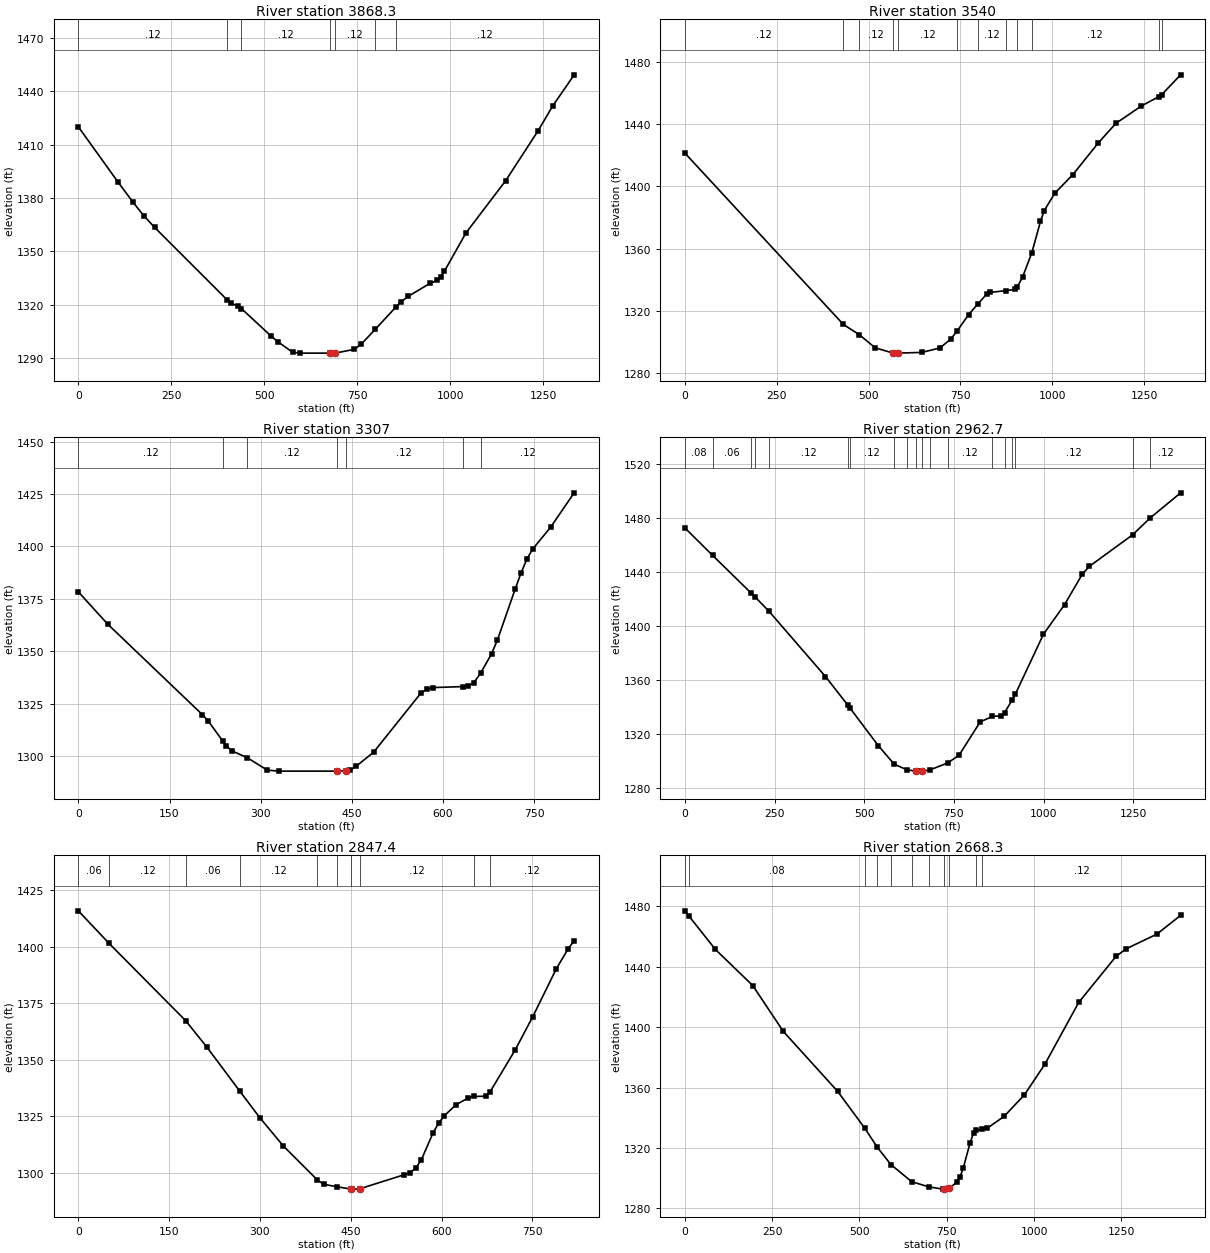
Type RM Length L Ch R = 1 ,3868.3  ,315.3,328.3,297.1
XS GIS Cut Line= 3
     1818969.166      252843.468     1818285.485      252854.786
     1817635.832      252848.676
#Sta/Elev= 30
       0 1419.96   107.4 1388.72   146.5 1377.76   175.8 1370.04   205.1 1363.44
  400.591322.634   410.3  1320.9   429.8 1319.14  438.571317.825   517.7  1302.5
   537.2 1299.07   576.3  1293.3   595.9 1292.79   676.3 1292.79   691.3 1292.81
     742  1294.9   761.4 1297.94  798.681306.193  853.841318.636     868 1321.61
   887.4 1324.73   945.6 1331.96     965 1333.66   974.7 1335.62   984.4 1338.78
  1042.6 1360.36  1149.2 1389.66  1236.5 1417.73  1275.3  1431.5  1333.5 1449.17
#Mann= 7 ,-1 , 0
       0     .12       0  400.59    .016       0  438.57     .12       0
   676.3    .045       0   691.3     .12       0  798.68     .06       0
  853.84     .12       0
Bank Sta=676.3,691.3
XS Rating Curve= 0 ,0
Exp/Cntr=0.3,0.1

Type RM Length L Ch R = 1 ,3540    ,125.6,232.9,232.8
XS GIS Cut Line= 2
      1818940.52      252666.384     1817591.561       252663.78
#Sta/Elev= 30
       0 1421.53  431.521311.213  474.761304.654   518.1 1296.19   565.1 1292.95
   576.7 1292.79   580.1 1292.79   645.2 1293.26     694 1296.12   723.4 1301.75
  741.611307.265   772.2 1317.56  797.361324.435   821.1 1330.68   830.9 1331.86
  874.821333.019   899.3 1333.82  904.361335.297   918.9 1341.64   944.31357.469
   967.7 1377.51   977.5  1384.3  1006.8 1395.72  1055.7 1407.58  1124.1 1427.77
    1173 1440.63  1241.4 1451.64 1288.821457.702 1297.411459.054    1349 1471.82
#Mann= 12 ,-1 , 0
       0     .12       0  431.52    .016       0  474.76     .12       0
   565.1    .045       0   580.1     .12       0  741.61     .06       0
  797.36     .12       0  874.82     .08       0  904.36     .06       0
   944.3     .12       0 1288.82     .06       0 1297.41     .12       0
Bank Sta=565.1,580.1
XS Rating Curve= 0 ,0
Exp/Cntr=0.3,0.1

Type RM Length L Ch R = 1 ,3307    ,250.9,344.4,338.9
XS GIS Cut Line= 3
     1818673.846      252458.326     1818434.045      252564.663
      1817880.66      252562.493
#Sta/Elev= 30
       0 1378.32    48.6 1362.83     204 1319.76   213.7 1316.71  237.561307.164
   242.9    1305   252.6 1302.46  278.181299.156   310.9 1293.25   330.3 1292.79
   424.8 1292.79   439.8 1292.91   446.8  1293.2   456.5    1295   485.6 1301.75
   563.3 1329.92     573  1331.9   582.7 1332.64  632.35 1333.12     641 1333.35
   650.7 1335.04  661.891339.543   679.8 1348.78   689.5 1355.37   718.6 1379.62
   728.3 1387.34     738 1394.01   747.8 1398.85   776.9 1409.12   815.7 1425.56
#Mann= 7 ,-1 , 0
       0     .12       0  237.56    .016       0  278.18     .12       0
   424.8    .045       0   439.8     .12       0  632.35     .08       0
  661.89     .12       0
Bank Sta=424.8,439.8
XS Rating Curve= 0 ,0
Exp/Cntr=0.3,0.1

Type RM Length L Ch R = 1 ,2962.7  ,122.6,115.3,108
XS GIS Cut Line= 2
     1818931.405      252197.634     1817582.331      252495.516
#Sta/Elev= 30
       0 1472.84   77.421452.441  184.831424.552  195.561421.774  234.181411.193
   391.9 1362.81  454.991341.359  460.351339.434   538.9 1311.75  583.121297.997
  619.751293.693   645.4  1292.8   646.7 1292.79   660.4 1292.79  682.371293.617
  733.191298.936   764.3 1304.58   823.1 1329.24  857.181333.239   881.8 1333.78
  891.231336.099   912.51345.563  921.371349.891   999.4 1394.08  1058.2 1415.99
  1107.2 1438.33  1126.8 1444.22 1247.771467.648 1296.831480.135  1381.6 1498.72
#Mann= 19 ,-1 , 0
       0     .08       0   77.42     .06       0  184.83     .08       0
  195.56     .06       0  234.18     .12       0  454.99     .06       0
  460.35     .12       0  583.12    .016       0  619.75     .12       0
   645.4    .045       0   660.4     .12       0  682.37     .06       0
  733.19     .12       0  857.18     .08       0  891.23     .12       0
   912.5     .06       0  921.37     .12       0 1247.77     .06       0
 1296.83     .12       0
Bank Sta=645.4,660.4
XS Rating Curve= 0 ,0
Exp/Cntr=0.3,0.1

Type RM Length L Ch R = 1 ,2847.4  ,168.4,179.1,188
XS GIS Cut Line= 4
     1818700.973      252138.231     1818336.389      252182.718
      1818116.12      252314.012     1817925.148      252354.159
#Sta/Elev= 30
       0    1416   50.951401.539  177.221367.387   212.6 1355.56  266.721336.141
   299.6 1324.47   338.3 1311.98  394.811296.853   405.3 1294.95  426.831293.854
   449.8 1292.85   452.8  1292.8   464.8 1292.95   538.2 1299.17   547.7 1300.11
   557.2 1302.03   566.7 1305.89   585.7 1317.62   595.2 1322.08   604.7 1325.38
   623.7 1330.12   643.2 1333.08  652.721333.818   672.5 1333.93   680.11335.915
   721.3 1354.33   750.6 1369.17   789.6 1390.43   809.1 1399.24   818.9 1402.76
#Mann= 10 ,-1 , 0
       0     .06       0   50.95     .12       0  177.22     .06       0
  266.72     .12       0  394.81    .016       0  426.83     .12       0
   449.8    .045       0   464.8     .12       0  652.72     .08       0
   680.1     .12       0
Bank Sta=449.8,464.8
XS Rating Curve= 0 ,0
Exp/Cntr=0.3,0.1

Type RM Length L Ch R = 1 ,2668.3  ,296.2,300,304.2
XS GIS Cut Line= 3
     1818910.029      252030.723      1818163.54      252089.649
     1817498.883      252180.169
#Sta/Elev= 30
       0 1476.99   12.741473.266    87.5 1451.46   194.5 1427.55     282 1397.19
   437.6 1357.52  515.57 1333.02  550.531320.693  590.051309.078  649.241297.781
  698.151294.318   739.1  1292.8   741.3 1292.81   756.3 1293.26     778 1297.19
   787.7 1300.64   797.4  1306.9   816.9 1323.48   826.6 1329.94  832.861331.728
  851.751332.448   865.5 1333.06   914.1 1340.92   972.4 1355.22  1030.7 1375.38
    1128 1416.43  1234.9 1446.91  1264.1  1451.9  1351.6 1461.56  1419.6 1473.98
#Mann= 11 ,-1 , 0
       0     .12       0   12.74     .08       0  515.57     .12       0
  550.53     .08       0  590.05     .06       0  649.24    .016       0
  698.15     .12       0   741.3    .045       0   756.3     .12       0
  832.86     .08       0  851.75     .12       0
Bank Sta=741.3,756.3
XS Rating Curve= 0 ,0
Exp/Cntr=0.3,0.1

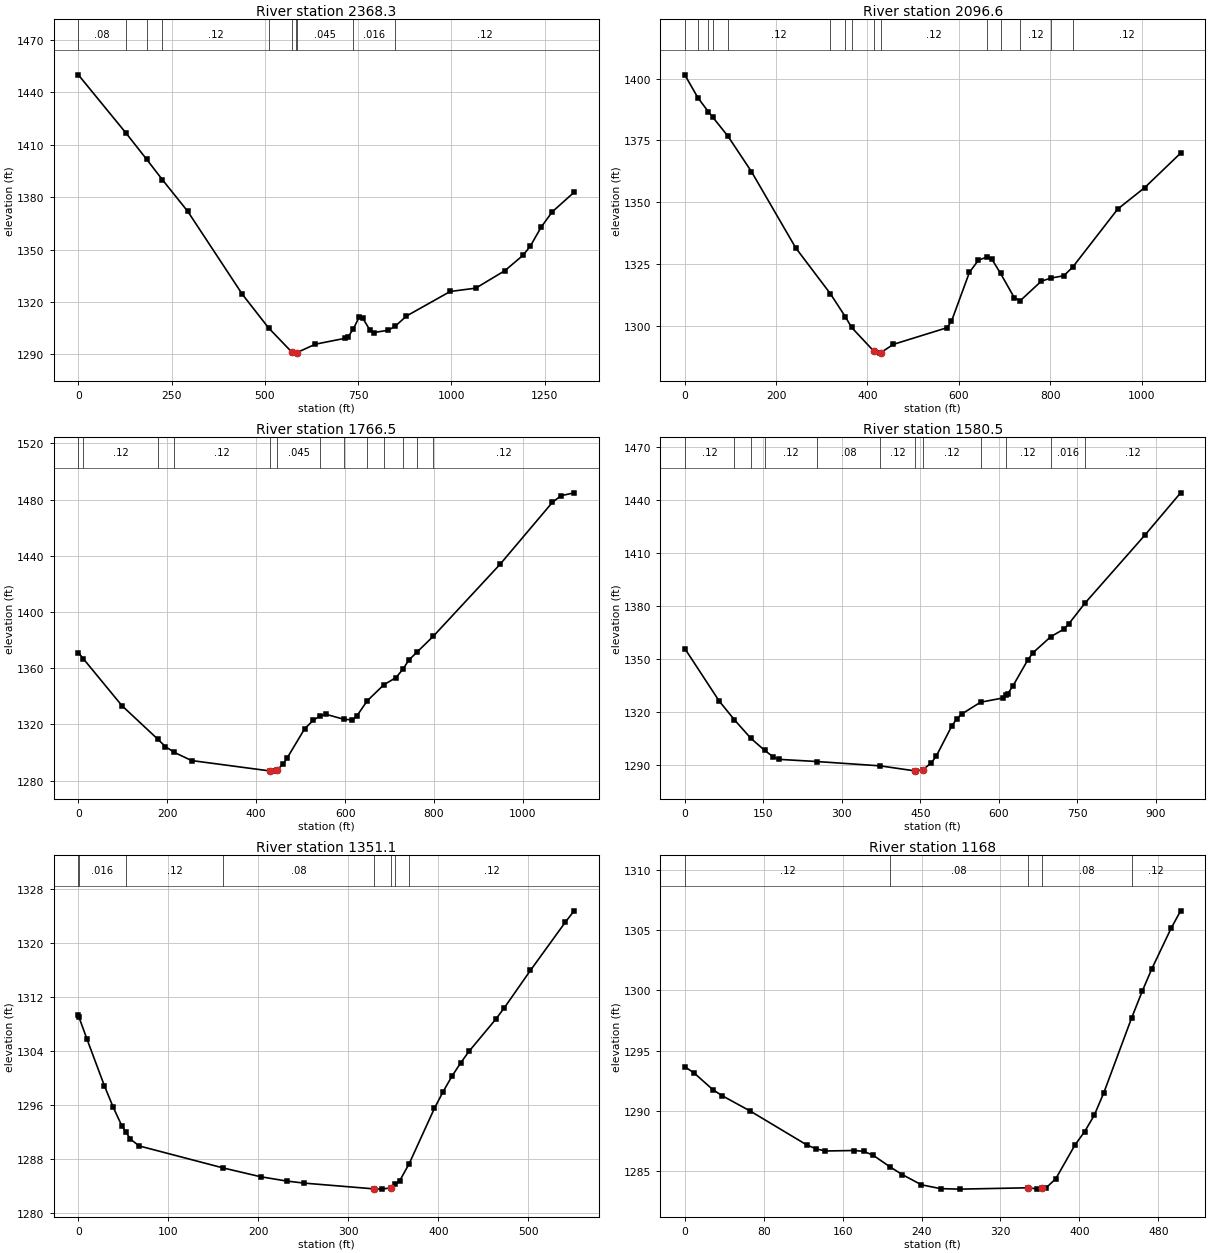
Type RM Length L Ch R = 1 ,2368.3  ,282.4,271.7,260.6
XS GIS Cut Line= 3
     1818827.238      251861.697     1818251.216      251831.493
     1817499.678      251790.619
#Sta/Elev= 30
       0 1450.01   127.81416.665  183.421401.581  225.571389.906   293.3 1371.87
   439.9 1324.33  510.151305.112  573.47 1291.06   576.8 1290.69   584.3 1290.96
   586.6 1291.04   635.5  1295.8   713.7 1299.11   723.4  1300.1  736.931304.318
   752.8 1311.27   762.5 1310.71   782.1 1303.83   791.9 1302.47     831 1303.79
  850.271306.205   879.8 1311.92   997.1 1325.98  1065.6 1327.88  1143.7  1337.9
  1192.6 1346.72  1212.2 1352.02  1241.5 1362.99  1270.8 1371.59  1329.5 1382.81
#Mann= 10 ,-1 , 0
       0     .08       0   127.8     .12       0  183.42     .08       0
  225.57     .12       0  510.15    .016       0  573.47    .045       0
   584.3     .12       0   586.6    .045       0  736.93    .016       0
  850.27     .12       0
Bank Sta=573.47,586.6
XS Rating Curve= 0 ,0
Exp/Cntr=0.3,0.1

Type RM Length L Ch R = 1 ,2096.6  ,319.7,330.2,340.6
XS GIS Cut Line= 3
     1818631.926      251389.041     1818164.478      251605.187
     1817598.072      251674.197
#Sta/Elev= 30
       0 1401.56   28.581392.305   51.161386.711   60.881384.503    94.51376.706
   145.8 1362.42   242.9 1331.49  318.611312.975  351.551303.599  365.051299.328
   414.4 1289.57   427.6 1288.89   429.4 1289.12   456.7 1292.44     574 1299.17
   583.9 1301.79   623.2 1321.61   642.9 1326.52  661.691327.802   672.4 1326.88
  691.381321.141   721.6 1311.29  734.561310.142   780.6 1318.02  801.751319.272
   829.8 1320.22  849.111323.664   947.9 1347.22  1006.9 1355.89  1085.6 1369.86
#Mann= 15 ,-1 , 0
       0     .12       0   28.58     .06       0   51.16     .08       0
   60.88     .06       0    94.5     .12       0  318.61    .016       0
  351.55     .06       0  365.05     .12       0   414.4    .045       0
   429.4     .12       0  661.69     .06       0  691.38    .016       0
  734.56     .12       0  801.75    .016       0  849.11     .12       0
Bank Sta=414.4,429.4
XS Rating Curve= 0 ,0
Exp/Cntr=0.3,0.1

Type RM Length L Ch R = 1 ,1766.5  ,186.2,186,185.8
XS GIS Cut Line= 3
     1818551.197      251267.947     1818210.051      251301.801
     1817437.888      251284.955
#Sta/Elev= 30
       0 1371.07   11.391366.644      98 1333.32  179.211309.285   195.9 1304.14
  216.141299.982   254.7 1294.22   430.8 1286.82   440.6 1286.69   447.9 1287.82
   460.1 1291.54   469.9 1296.15     509 1316.83   528.6 1322.98  543.941326.028
   557.9 1327.07  596.961323.624   616.6 1323.15   626.3 1325.92   649.81336.756
  687.431348.247   714.3 1353.22  730.131359.285   743.7 1365.88  761.281371.295
  798.091382.618     949 1434.11  1066.3 1478.06  1085.8  1482.8  1115.2 1484.83
#Mann= 13 ,-1 , 0
       0     .06       0   11.39     .12       0  179.21    .016       0
  216.14     .12       0   430.8    .045       0   447.9    .045       0
  543.94     .08       0  596.96    .016       0   649.8     .12       0
  687.43    .016       0  730.13     .12       0  761.28    .016       0
  798.09     .12       0
Bank Sta=430.8,447.9
XS Rating Curve= 0 ,0
Exp/Cntr=0.3,0.1

Type RM Length L Ch R = 1 ,1580.5  ,216.8,229.3,241.2
XS GIS Cut Line= 3
      1818532.28      251196.173     1818404.242      251118.048
     1817606.709      251106.673
#Sta/Elev= 30
       0 1355.74    65.6 1326.03   94.641315.424  126.55 1304.79  152.431298.109
   169.4 1294.26   179.2 1292.97  252.391291.732  373.351289.269     440 1286.42
   441.8 1286.29     455 1287.13     471  1290.9   480.7 1294.84   509.9 1311.65
   519.6 1315.89   529.3 1318.64  565.171325.317   607.2 1327.68  613.491329.184
   616.9    1330   626.6 1334.29   655.8 1349.42   665.5 1353.36  699.711362.517
   723.9  1366.6   733.6 1369.61  764.371381.299   879.5 1420.04   947.6 1443.94
#Mann= 12 ,-1 , 0
       0     .12       0   94.64     .06       0  126.55    .016       0
  152.43     .12       0  252.39     .08       0  373.35     .12       0
     440    .045       0     455     .12       0  565.17     .08       0
  613.49     .12       0  699.71    .016       0  764.37     .12       0
Bank Sta=440,455
XS Rating Curve= 0 ,0
Exp/Cntr=0.3,0.1

Type RM Length L Ch R = 1 ,1351.1  ,194.8,183.1,170.7
XS GIS Cut Line= 3
     1818458.496      251077.901     1818114.087      250864.269
     1817969.129      250877.163
#Sta/Elev= 29
       0 1309.29     .721309.027     9.6 1305.78      29 1298.86    38.6 1295.75
    48.2 1292.98   52.561292.081    57.9 1290.98    67.6 1289.98  160.97 1286.72
   202.6 1285.42   231.6 1284.78   250.9 1284.48   328.1 1283.63     337 1283.59
   347.4 1283.79     352 1284.28     357 1284.82  367.561287.363   395.6 1295.55
   405.3 1298.03     415 1300.28   424.7 1302.26   434.4 1304.04   463.5 1308.69
   473.2 1310.41   502.3 1315.96   541.1  1323.1   550.8 1324.76
#Mann= 8 ,-1 , 0
       0     .06       0     .72    .016       0   52.56     .12       0
  160.97     .08       0   328.1    .045       0   347.4    .045       0
     352     .08       0  367.56     .12       0
Bank Sta=328.1,347.4
XS Rating Curve= 0 ,0
Exp/Cntr=0.3,0.1

Type RM Length L Ch R = 1 ,1168    ,451.4,453.9,454.4
XS GIS Cut Line= 3
     1818533.366      250630.852     1818423.774      250721.998
     1818065.701      250759.975
#Sta/Elev= 30
       0 1293.66     9.5 1293.14    28.5 1291.75      38 1291.25    66.5 1289.97
   123.5 1287.17     133 1286.84   142.5 1286.66   171.7  1286.7   181.5 1286.63
   191.2 1286.29  208.051285.339   220.4  1284.7   239.9 1283.85   259.3 1283.53
   278.8 1283.49   347.5  1283.6   356.6 1283.52   362.5 1283.57   366.4 1283.61
   376.1 1284.36   395.6 1287.17   405.3 1288.27     415 1289.62   424.8 1291.51
  453.051297.745   463.7 1299.94   473.4  1301.8   492.9 1305.16   502.6 1306.62
#Mann= 5 ,-1 , 0
       0     .12       0  208.05     .08       0   347.5    .045       0
   362.5     .08       0  453.05     .12       0
Bank Sta=347.5,362.5
XS Rating Curve= 0 ,0
Exp/Cntr=0.3,0.1

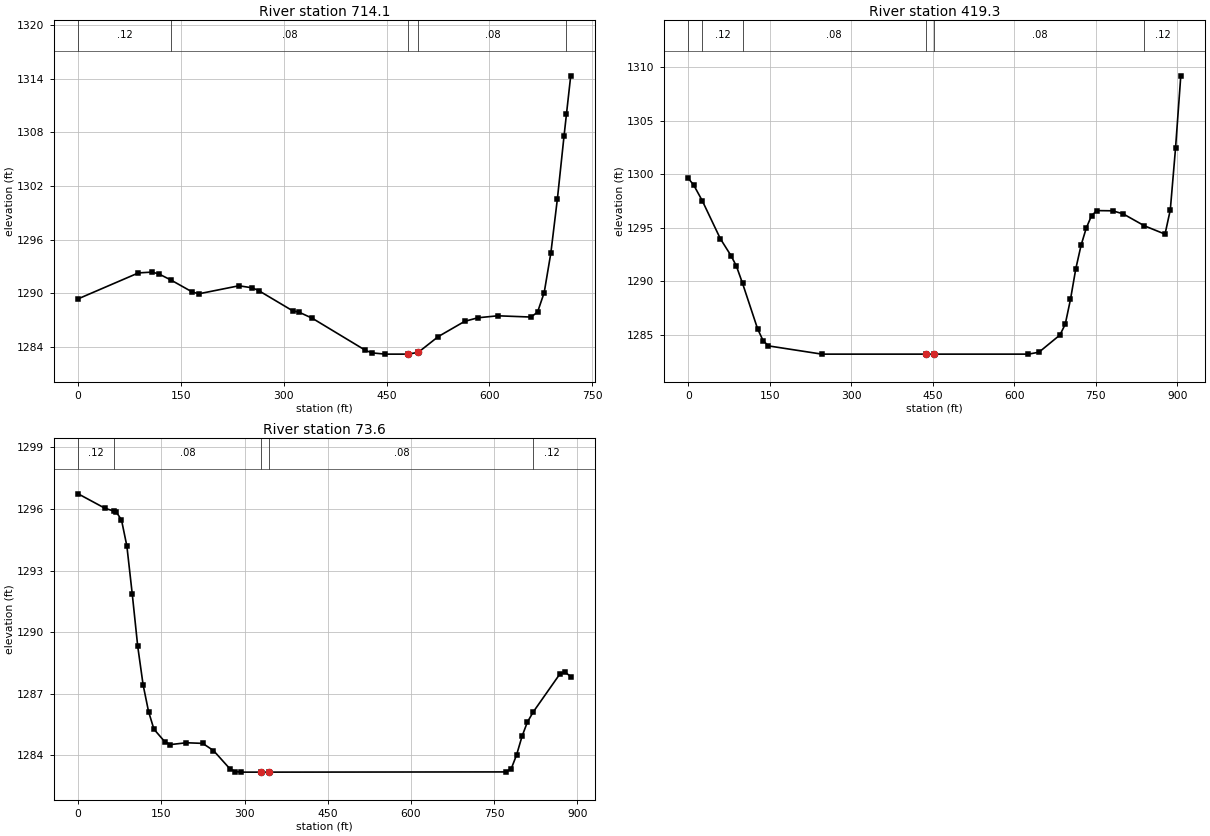
Type RM Length L Ch R = 1 ,714.1   ,298.2,294.7,288.7
XS GIS Cut Line= 3
     1818422.645      250646.376     1818341.916      250344.292
     1817938.704      250297.851
#Sta/Elev= 30
       0 1289.38    87.9 1292.28   107.5 1292.37   117.3 1292.18  135.131291.495
   166.1 1290.16   175.9 1289.94   234.5 1290.84   254.1 1290.61   263.8 1290.28
   312.7 1288.05   322.4 1287.88   341.7  1287.2     419 1283.62   428.6 1283.33
     448 1283.19   481.2 1283.19   496.2 1283.39   525.3 1285.15   563.9 1286.86
   583.3 1287.26   612.3 1287.48   660.6 1287.34   670.2 1287.89   679.9 1290.08
   689.6  1294.5   699.2  1300.6   708.9 1307.64  712.371310.037   718.6 1314.34
#Mann= 5 ,-1 , 0
       0     .12       0  135.13     .08       0   481.2    .045       0
   496.2     .08       0  712.37     .12       0
Bank Sta=481.2,496.2
XS Rating Curve= 0 ,0
Exp/Cntr=0.3,0.1

Type RM Length L Ch R = 1 ,419.3   ,348.1,345.7,340.8
XS GIS Cut Line= 3
     1818847.992      250183.702     1818405.798      250199.805
     1817941.959      250207.574
#Sta/Elev= 30
       0 1299.61     9.8 1299.01   25.891297.514      59 1293.98    78.7 1292.39
    88.5 1291.43   99.881289.811   127.8 1285.53   137.7 1284.46   147.5 1283.96
   245.8 1283.19   437.6 1283.19   452.6 1283.19   626.1 1283.19   645.4 1283.37
   684.1 1284.98   693.8 1285.99   703.4  1288.3   713.1 1291.14   722.8 1293.34
   732.4 1294.96   742.1 1296.12   751.8  1296.6   780.8 1296.58   800.1  1296.3
   839.61295.173   877.4  1294.4   887.1 1296.67   896.7 1302.41   906.4 1309.19
#Mann= 6 ,-1 , 0
       0     .08       0   25.89     .12       0   99.88     .08       0
   437.6    .045       0   452.6     .08       0   839.6     .12       0
Bank Sta=437.6,452.6
XS Rating Curve= 0 ,0
Exp/Cntr=0.3,0.1

Type RM Length L Ch R = 1 ,73.6    ,65.9,73.6,81
XS GIS Cut Line= 2
     1818888.046       249885.84     1818023.462      250088.965
#Sta/Elev= 30
       0 1296.74    48.8 1296.03   65.251295.895    68.3 1295.87    78.1 1295.47
    87.8  1294.2    97.6 1291.84   107.4 1289.31   117.1 1287.44   126.9 1286.14
   136.6 1285.28   156.2 1284.67   165.9 1284.53   195.2 1284.62   224.5 1284.59
     244 1284.24   273.3 1283.36     283 1283.22   292.8 1283.19   329.5 1283.19
   344.5 1283.19     771  1283.2   780.8 1283.35   790.5 1284.03   800.3 1284.93
     810 1285.63  820.871286.133   868.6 1287.97   878.4 1288.05   888.1 1287.84
#Mann= 5 ,-1 , 0
       0     .12       0   65.25     .08       0   329.5    .045       0
   344.5     .08       0  820.87     .12       0
Bank Sta=329.5,344.5
XS Rating Curve= 0 ,0
Exp/Cntr=0.3,0.1

Chan Stop Cuts=-1
Use User Specified Reach Order=0
Composite Channel Slope=5